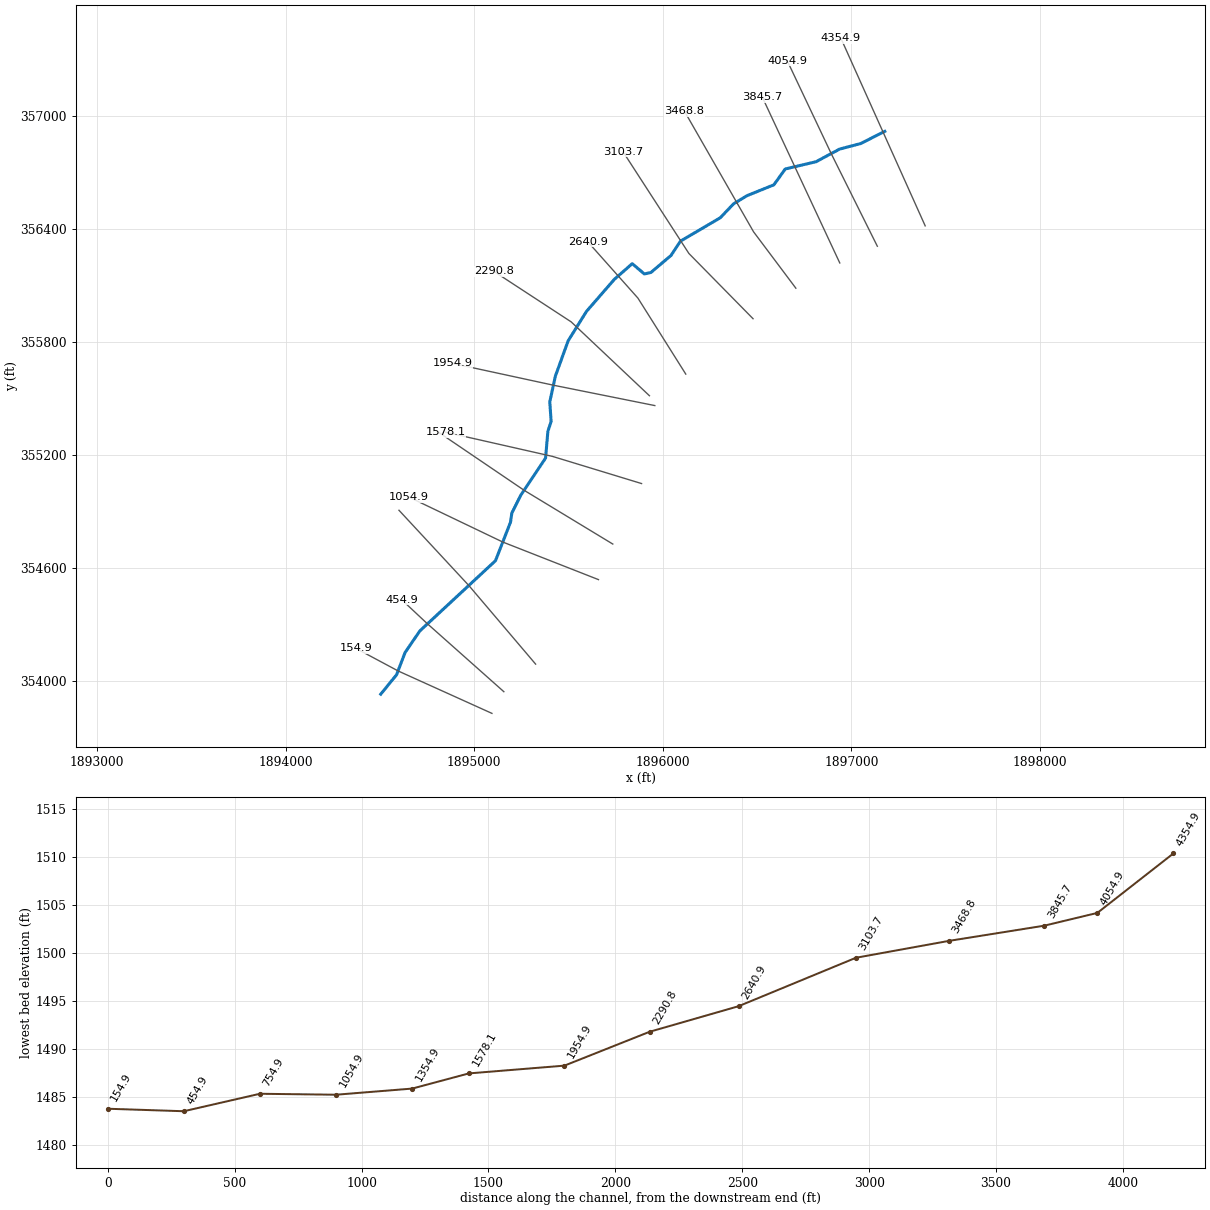
--- LickFork.prj (project) ---

Proj Title=LickFork
Current Plan=p01
Default Exp/Contr=0,0
English Units
Geom File=g01
Flow File=f01
Plan File=p01
BEGIN DESCRIPTION:
END DESCRIPTION:
DSS Export Rating Curves= 0
DSS Export Rating Curve Sorted= 0
DSS Export Volume Flow Curves= 0
DXF OffsetX= 0
DXF OffsetY= 0
DXF ScaleX= 0
DXF ScaleY= 0

--- LickFork.p01 (plan) ---

Plan Title=Floodplain
Program Version=4.00
Geom File=g01
Flow File=f01
K Sum by GR=0
Std Step Tol=0.01
Critical Tol=0.01
Num of Std Step Trials=20
Max Error Tol=0.3
Flow Tol Ratio=0.001
Split Flow NTrial=30
Split Flow Tol=0.02
Split Flow Ratio=0.02
Log Output Level=0
Friction Slope Method=1
Unsteady Friction Slope Method=2
Unsteady Bridges Friction Slope Method=1
Global Log Level=0
CheckData=False
Run HTab=0
Run UNet=0
Run PostProcess=0
UNET Theta=0
UNET Theta Warmup=0
UNET ZTol=0
UNET ZSATol=0
UNET MxIter=0
UNET MaxInSteps=0
UNET DtIC=0
UNET DtMin=0
UNET MaxCRTS=0
UNET WFStab=0
UNET SFStab=0
UNET WFX=0
UNET SFX=0
UNET DSS MLevel=0
UNET DZMax Abort=0
UNET Convert EG Bridges=0
UNET Use Existing IB Tables=0
UNET Froude Limit=0
UNET Froude Power=0
Write IC File=0
Echo Input=False
Echo Output=False
Write Detailed=0

--- LickFork.f01 (steady flow) ---

Flow Title=NFF Regression Equation
Program Version=4.00
Number of Profiles=1
Profile Names=P100yr
River Rch & RM=LickFork,Main      ,4354.9
1152.183
River Rch & RM=LickFork,Main      ,154.9
1237.828
Boundary for River Rch & Prof#=LickFork,Main      ,1
Up Type=0
Dn Type=3
Dn Slope=0.001619

--- LickFork.g01 (geometry) ---

Geom Title=USGS 3m DEM
Program Version=4.10

River Reach=LickFork        ,Main
Reach XY= 30
     1897176.873      356920.794     1897049.009       356855.81
     1896937.447      356826.518     1896812.289      356759.336
      1896649.04      356720.744     1896588.828      356636.658
      1896445.97       356578.78     1896374.789      356535.378
     1896304.694      356461.593     1896093.539      356337.461
     1896043.192      356261.072     1895936.849      356170.866
     1895902.018      356163.058     1895837.753      356217.669
     1895742.845      356134.336     1895595.275      355964.197
     1895498.053      355807.947     1895430.345      355620.447
     1895400.625      355483.403     1895407.775      355379.128
     1895390.619      355327.335     1895378.261      355184.683
     1895246.317      354986.766     1895199.442      354893.016
     1895192.498      354844.405     1895112.779       354639.51
     1894711.595       354266.28      1894633.47      354151.697
     1894588.205       354033.49     1894504.478      353930.477

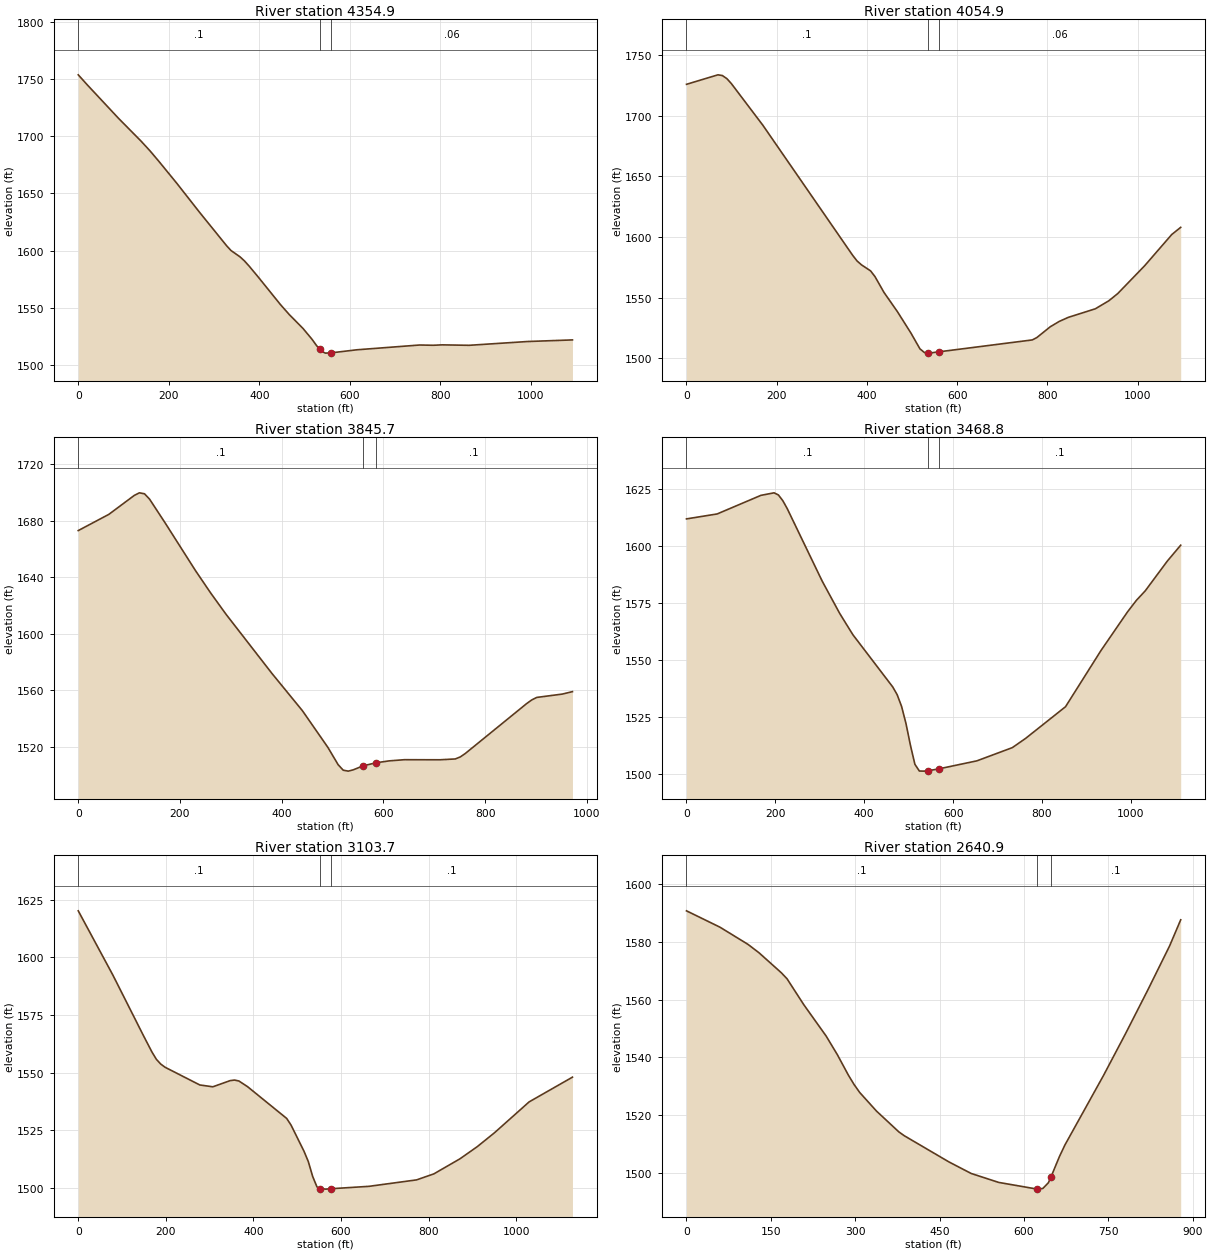
Type RM Length L Ch R = 1 ,4354.9  ,298.8,299.9,300.4
XS GIS Cut Line= 3
     1897391.092      356418.473     1897167.747      356916.704
     1896944.403      357414.934
#Sta/Elev= 30
       0 1753.47    19.8 1744.78    89.4 1715.31     139 1695.47   158.8 1686.95
   178.7 1677.64   218.4 1658.41     268  1633.4   327.6 1604.27   337.5    1600
   357.4 1594.49   367.3  1590.9   377.2 1586.56   397.1 1577.13   446.7 1552.81
   466.6 1543.91   496.4 1532.01   516.2 1522.62   526.2 1517.16   533.5 1513.55
   536.1 1512.27     546 1510.36   558.5 1510.58   615.5 1513.27   754.5 1517.45
   784.2 1517.22   804.1 1517.58   863.7 1517.19   992.7  1520.5    1092  1521.9
#Mann= 3 , 0 , 0
       0      .1       0   533.5    .045       0   558.5     .06       0
Bank Sta=533.5,558.5
XS Rating Curve= 0 ,0
Exp/Cntr=0.3,0.1

Type RM Length L Ch R = 1 ,4054.9  ,209.8,209.2,209.1
XS GIS Cut Line= 3
      1897137.35      356310.269     1896893.717      356800.489
     1896659.424      357296.307
#Sta/Elev= 30
       0    1726    69.7 1733.83    79.6 1733.23    89.6 1730.65    99.5 1726.58
   169.2 1692.29   368.3 1584.96   378.2 1580.21   388.2 1576.96   408.1 1572.06
     418 1567.28   437.9 1554.26   467.8 1538.31   497.7 1520.68   517.6  1507.7
   527.5 1504.67   534.9 1504.29   537.5 1504.16   559.9 1505.24   766.8 1515.06
   776.8    1517   806.7 1525.95   826.6 1530.34   846.5 1533.67   906.4 1540.73
   936.3 1547.33   956.2 1553.31    1016 1576.33  1075.9 1602.03  1095.8 1607.97
#Mann= 3 , 0 , 0
       0      .1       0   534.9    .045       0   559.9     .06       0
Bank Sta=534.9,559.9
XS Rating Curve= 0 ,0
Exp/Cntr=0.3,0.1

Type RM Length L Ch R = 1 ,3845.7  ,374.8,376.9,379
XS GIS Cut Line= 2
     1896938.139      356221.473     1896527.662      357101.993
#Sta/Elev= 30
       0 1673.03    60.1 1684.49   110.2 1697.92   120.2 1699.74   130.2 1699.07
   140.2 1695.27   170.3 1678.74   230.4 1644.74   260.4 1628.83   290.4 1613.86
   380.6 1572.03   440.7 1545.56   490.8 1519.59   510.8 1507.44   520.8 1503.49
   530.8 1502.83   540.8 1503.77     560 1506.56     585 1508.71   610.9 1510.07
     641 1510.91   711.1 1510.86   741.1 1511.44   751.2 1512.91   761.2 1515.41
   881.4  1550.6   891.4 1553.19   901.4 1554.98   951.5 1557.34   971.5 1559.08
#Mann= 3 , 0 , 0
       0      .1       0     560    .045       0     585      .1       0
Bank Sta=560,585
XS Rating Curve= 0 ,0
Exp/Cntr=0.3,0.1

Type RM Length L Ch R = 1 ,3468.8  ,363.5,364.9,366.4
XS GIS Cut Line= 3
     1896705.303      356087.373     1896480.979      356387.154
     1896114.806      357027.591
#Sta/Elev= 30
       0 1612.03      69  1614.2   167.5 1622.37   197.1 1623.48   206.9 1622.54
   216.8 1620.01   226.6 1616.59   305.4 1584.69   344.9 1570.47   374.4 1561.17
   464.1 1538.23   474.1 1534.81   484.1 1529.63     494 1522.11     504 1512.57
     514 1504.25     524 1501.29   533.9 1501.24   543.7 1501.39   568.7 1502.27
   653.6 1505.76   733.3 1511.56   763.2 1515.62     853 1529.53   932.7 1554.19
   992.5 1571.18  1012.4 1576.23  1032.4 1580.43  1082.2 1593.53  1112.2 1600.48
#Mann= 3 , 0 , 0
       0      .1       0   543.7    .045       0   568.7      .1       0
Bank Sta=543.7,568.7
XS Rating Curve= 0 ,0
Exp/Cntr=0.3,0.1

Type RM Length L Ch R = 1 ,3103.7  ,455.6,462.7,466.9
XS GIS Cut Line= 3
     1896478.393      355925.158     1896138.148      356271.904
     1895789.482      356811.681
#Sta/Elev= 30
       0 1620.19    79.3 1592.24   148.7 1566.13   168.5 1558.88   178.5 1555.76
   188.4 1553.72   198.3 1552.34   277.6 1544.66   307.3 1543.87     347 1546.56
   356.9 1546.79   366.8 1546.39   386.7 1543.91   475.9 1530.15   485.8 1527.29
   515.5  1515.9   525.3 1511.44   535.2 1505.01   545.1 1500.44   552.5 1499.75
   564.9 1499.49   577.5 1499.67   663.8  1500.7   772.5  1503.5     812 1506.11
   871.4 1512.62   910.9 1517.89   950.4 1523.94  1029.5 1537.33  1128.4 1548.05
#Mann= 3 , 0 , 0
       0      .1       0   552.5    .045       0   577.5      .1       0
Bank Sta=552.5,577.5
XS Rating Curve= 0 ,0
Exp/Cntr=0.3,0.1

Type RM Length L Ch R = 1 ,2640.9  ,347.7,350.1,352.4
XS GIS Cut Line= 3
     1896121.637      355630.956     1895867.957      356034.689
     1895600.987      356335.213
#Sta/Elev= 30
       0 1590.75    59.6 1585.08   109.3 1579.15   129.1 1576.21   168.9 1569.27
   178.8 1567.23   208.6 1558.26   248.3 1547.42   268.2 1540.99   288.1 1533.81
     298 1530.65   307.9 1527.91   337.7 1521.48   377.5 1514.27   387.4  1512.9
   466.9 1503.83   506.2 1499.86   555.2 1496.76     623 1494.47   623.9 1494.44
   633.7 1494.68   643.5 1496.64     648 1498.59   663.1 1505.68   672.9 1509.71
   741.5 1533.76   780.8 1548.28     820 1563.23   859.2 1578.66   878.8 1587.64
#Mann= 3 , 0 , 0
       0      .1       0     623    .045       0     648      .1       0
Bank Sta=623,648
XS Rating Curve= 0 ,0
Exp/Cntr=0.3,0.1

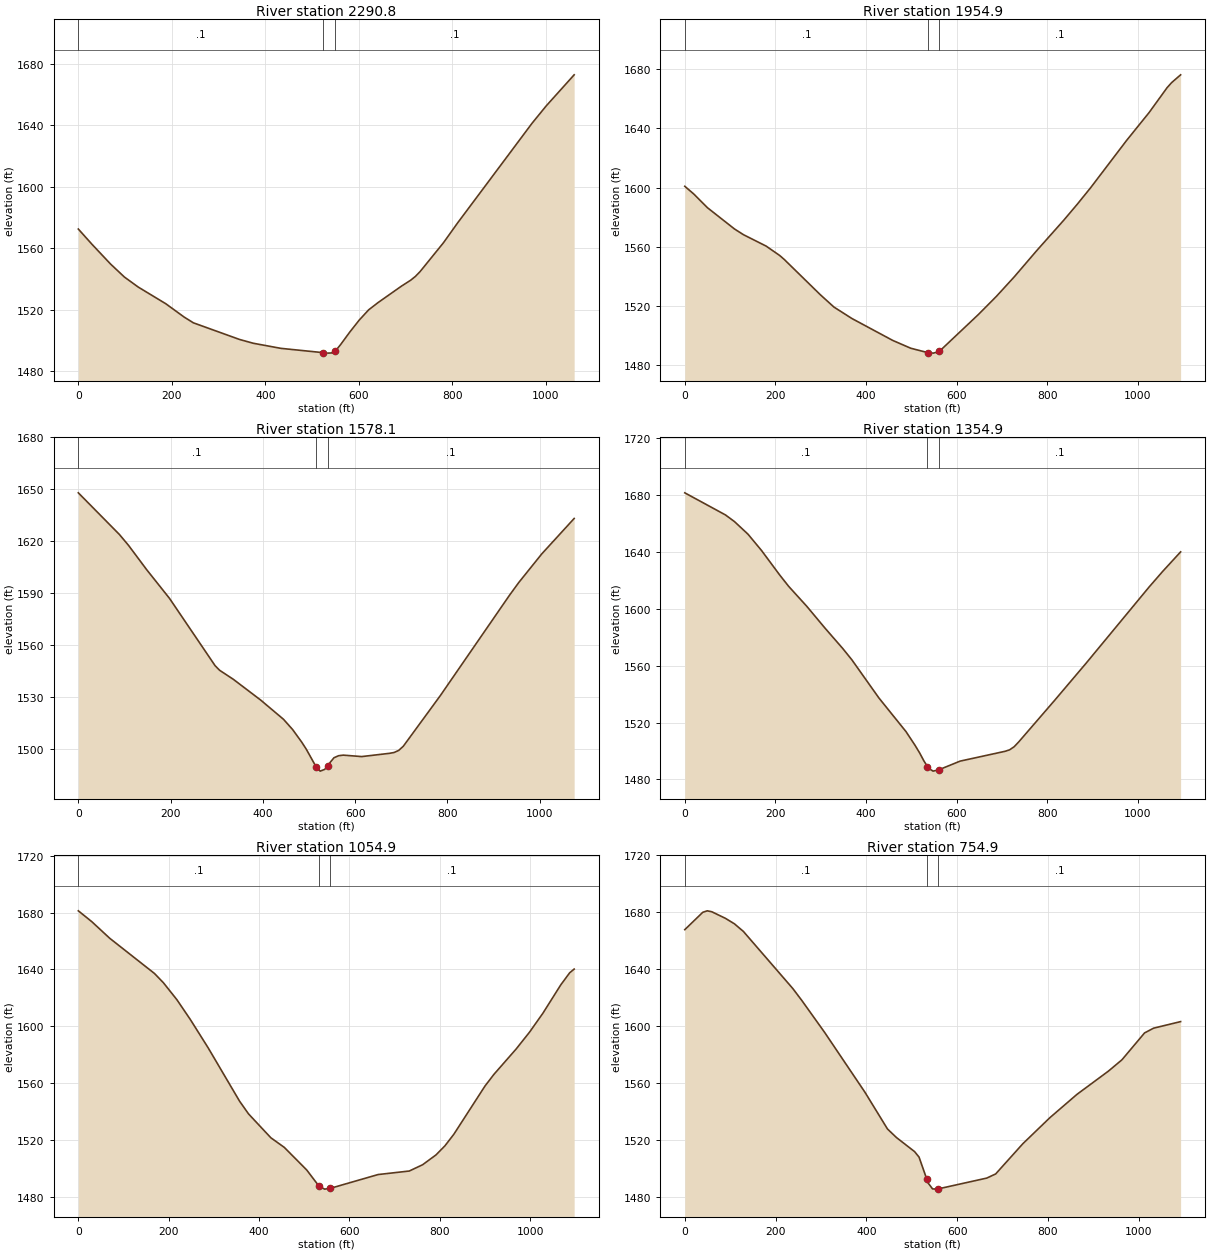
Type RM Length L Ch R = 1 ,2290.8  ,320.5,335.9,350.9
XS GIS Cut Line= 3
     1895928.986      355515.981     1895514.122      355908.384
     1895104.543      356176.592
#Sta/Elev= 30
       0 1572.53    29.5 1562.52    68.9 1549.78    98.5 1541.32     128  1534.8
   187.1 1523.92   226.4 1515.24   246.1  1511.5   344.6  1500.7   374.1 1498.21
   433.2 1494.89   523.3  1492.1   531.7 1491.78   541.5 1491.89   548.3 1493.13
   551.4  1493.7   561.2 1497.41     581 1505.62     601 1513.33     621 1519.94
     641 1524.64   690.9 1535.32   710.9 1539.23   720.9 1541.68   730.9 1544.79
   780.9 1563.56   810.8 1576.31   970.7 1641.44  1000.7 1652.63  1060.6  1672.9
#Mann= 3 , 0 , 0
       0      .1       0   523.3    .045       0   548.3      .1       0
Bank Sta=523.3,548.3
XS Rating Curve= 0 ,0
Exp/Cntr=0.3,0.1

Type RM Length L Ch R = 1 ,1954.9  ,377.3,376.6,376.4
XS GIS Cut Line= 3
     1895957.541      355463.698     1895419.822      355571.923
     1894886.657      355687.548
#Sta/Elev= 30
       0 1600.84      20 1595.59    49.9 1586.41   109.7 1572.03   129.6 1568.16
   179.5 1560.48   209.4 1554.14   219.4 1551.49   299.2 1527.62   329.1 1519.34
     369 1511.57   458.8 1496.83   498.6 1491.55     536 1488.59   548.5 1488.25
   558.4 1489.07     561 1489.67   568.3 1491.35   647.7 1514.26   687.4  1526.5
     727 1539.73   776.6 1557.44   836.2 1577.94   865.9 1588.68   895.7 1599.95
     975 1631.83  1024.6 1650.63  1064.3 1667.42  1074.2  1670.8  1094.1 1676.07
#Mann= 3 , 0 , 0
       0      .1       0     536    .045       0     561      .1       0
Bank Sta=536,561
XS Rating Curve= 0 ,0
Exp/Cntr=0.3,0.1

Type RM Length L Ch R = 1 ,1578.1  ,232.1,223.2,212.9
XS GIS Cut Line= 3
     1895887.225      355049.384     1895414.556      355193.811
     1894848.278      355322.346
#Sta/Elev= 30
       0 1647.95      89 1623.94   108.7 1617.69   148.3 1603.58   197.7 1587.06
   296.6 1548.22   306.4 1545.59   336.1 1540.38   395.4 1528.41   444.8 1517.33
   464.6 1511.41   484.4 1504.12   494.2 1500.08   515.3    1490   524.3 1487.44
   534.3 1488.46   540.3 1490.68   554.3 1495.17   564.3 1496.33   574.3 1496.66
   614.4 1495.83   674.4  1497.7   684.5 1498.18   694.5 1499.37   704.5 1501.79
   784.6 1530.93   934.8  1588.9   954.8 1596.21  1004.8 1612.76  1074.9 1633.15
#Mann= 3 , 0 , 0
       0      .1       0   515.3    .045       0   540.3      .1       0
Bank Sta=515.3,540.3
XS Rating Curve= 0 ,0
Exp/Cntr=0.3,0.1

Type RM Length L Ch R = 1 ,1354.9  ,295.2,300,304.1
XS GIS Cut Line= 3
     1895734.703       354727.94     1895266.119      355012.595
     1894814.101      355319.871
#Sta/Elev= 30
       0 1681.46    89.7 1665.94   109.6 1661.27   139.6 1652.37   169.5  1640.9
   209.3 1623.82   229.3 1615.75   269.2 1601.76     309 1586.59   348.9 1571.99
   368.8 1564.14   428.6 1537.29   488.5  1513.6   508.4    1504   518.4 1498.72
   528.3 1492.86   535.8  1489.1   538.3 1487.85   548.3 1485.86   560.8 1486.78
   607.9 1492.89   707.3  1499.8   717.2 1500.83   727.2    1503   737.1  1506.3
   816.6  1535.6   886.2 1561.74  1025.3  1615.3  1055.1  1626.2  1094.8 1639.96
#Mann= 3 , 0 , 0
       0      .1       0   535.8    .045       0   560.8      .1       0
Bank Sta=535.8,560.8
XS Rating Curve= 0 ,0
Exp/Cntr=0.3,0.1

Type RM Length L Ch R = 1 ,1054.9  ,313.5,299.9,289.5
XS GIS Cut Line= 3
     1895658.797      354538.957     1895151.725       354738.46
     1894653.919      354977.432
#Sta/Elev= 30
       0 1681.24    29.7 1673.63    69.4 1661.93   168.4 1637.13   188.2 1630.61
     218 1618.68   247.7 1604.75   287.3 1584.73   356.7 1547.21   376.5 1538.25
     426 1521.39   455.7 1514.63   505.3 1498.73   532.4 1487.36   544.9 1485.22
   557.4 1485.76   663.2 1495.48   732.3 1497.97   761.8  1502.4   791.4 1509.32
   811.1  1515.7   830.9 1523.87   899.9 1557.88   919.6 1566.06   968.9 1583.98
   998.5 1595.84  1028.1 1609.19  1067.5  1629.1  1087.2 1637.59  1097.1 1640.21
#Mann= 3 , 0 , 0
       0      .1       0   532.4    .045       0   557.4      .1       0
Bank Sta=532.4,557.4
XS Rating Curve= 0 ,0
Exp/Cntr=0.3,0.1

Type RM Length L Ch R = 1 ,754.9   ,296.2,300,301.9
XS GIS Cut Line= 3
     1895325.564      354090.014     1894972.546      354506.393
     1894601.074      354907.421
#Sta/Elev= 30
       0 1667.74    39.7 1679.95    49.6 1680.97    59.6  1680.3    89.3 1675.73
   109.2 1671.87     129 1666.52   238.2 1626.26   258.1 1617.84   307.7  1595.7
     397 1553.41   446.6  1527.6   466.5 1521.56   506.2 1511.72   516.1 1507.87
   533.4 1492.13     536 1489.68   545.9 1485.49   555.8 1485.32   558.4 1485.49
   665.2 1493.07     685    1496   744.7 1517.19   804.3 1535.51   863.9 1551.89
   933.5  1568.3   963.3 1576.27    1013 1595.12  1032.9 1598.47  1092.5 1603.09
#Mann= 3 , 0 , 0
       0      .1       0   533.4    .045       0   558.4      .1       0
Bank Sta=533.4,558.4
XS Rating Curve= 0 ,0
Exp/Cntr=0.3,0.1

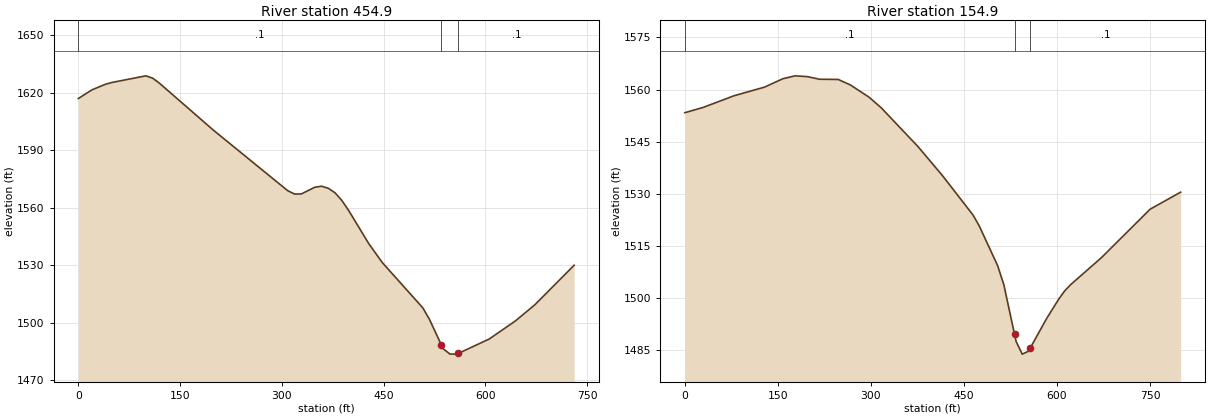
Type RM Length L Ch R = 1 ,454.9   ,291.5,299.6,306.6
XS GIS Cut Line= 3
     1895157.085      353943.439     1894748.082      354307.743
     1894614.483      354433.086
#Sta/Elev= 30
       0 1616.94    19.9 1621.44    39.8 1624.36    49.8 1625.34    99.6 1628.79
   109.5 1627.58   119.5 1624.96   199.2  1600.4   308.7 1568.82   318.7 1567.08
   328.6  1567.1   348.6 1570.63   358.5 1571.17   368.5 1570.08   378.4 1567.74
   388.4 1563.75   398.3 1558.61   428.2 1541.16   448.1  1531.3   507.9 1507.62
   517.8 1501.53   535.2 1488.26   537.8 1486.34   547.7 1483.55   557.4  1483.5
   560.2 1483.88   605.6 1491.37   644.1 1500.78   673.1 1509.31   730.9 1529.92
#Mann= 3 , 0 , 0
       0      .1       0   535.2    .045       0   560.2      .1       0
Bank Sta=535.2,560.2
XS Rating Curve= 0 ,0
Exp/Cntr=0.3,0.1

Type RM Length L Ch R = 1 ,154.9   ,164,155,148
XS GIS Cut Line= 3
     1895093.869       353828.29      1894598.31      354052.825
     1894373.243      354173.385
#Sta/Elev= 30
       0 1553.32    29.7 1554.84    79.1 1558.18   128.6 1560.69   158.3 1563.12
     178 1563.94   197.8  1563.7   217.6 1562.95   247.3  1562.9   267.1  1561.3
   296.8 1557.82   316.5 1554.77   375.9 1543.57   415.5 1535.18   464.9 1523.79
   474.8 1520.67   504.5 1509.21   514.4 1503.74   531.6 1489.49   534.2 1487.41
     544 1483.76   553.9 1484.57   556.6  1485.4   583.3    1494     603 1499.64
   612.8 1502.05   622.6 1503.86   671.7 1511.55   750.3 1525.52   799.4 1530.42
#Mann= 3 , 0 , 0
       0      .1       0   531.6    .045       0   556.6      .1       0
Bank Sta=531.6,556.6
XS Rating Curve= 0 ,0
Exp/Cntr=0.3,0.1

Chan Stop Cuts=-1
Use User Specified Reach Order=0
Composite Channel Slope=5